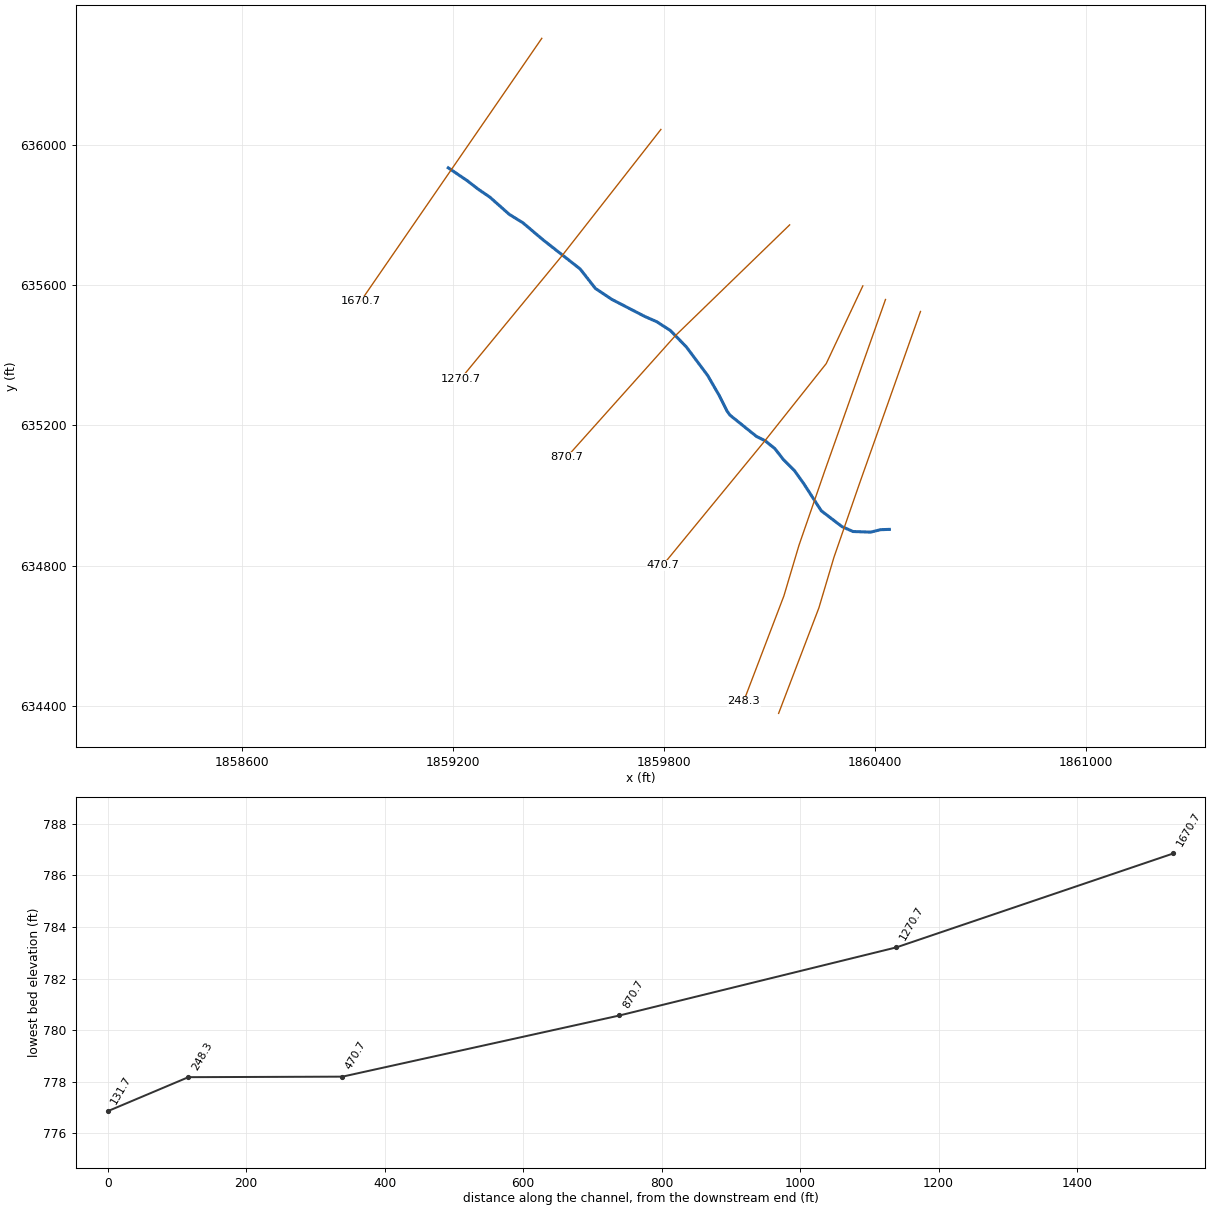
--- MissouriFk.prj (project) ---

Proj Title=MissouriFk
Current Plan=p01
Default Exp/Contr=0,0
English Units
Geom File=g01
Flow File=f01
Plan File=p01
BEGIN DESCRIPTION:
AMEC Environment & Infrastructure, 2013
Projection: NAD 1983 State Plane West Virginia South FIPS 4702 (US Feet)
Vertical Datum: NAVD 1988
END DESCRIPTION:
DSS Export Rating Curves= 0
DSS Export Rating Curve Sorted= 0
DSS Export Volume Flow Curves= 0
DXF OffsetX= 0
DXF OffsetY= 0
DXF ScaleX= 0
DXF ScaleY= 0

--- MissouriFk.p01 (plan) ---

Plan Title=Floodplain
Program Version=4.00
Geom File=g01
Flow File=f01
K Sum by GR=0
Std Step Tol=0.01
Critical Tol=0.01
Num of Std Step Trials=20
Max Error Tol=0.3
Flow Tol Ratio=0.001
Split Flow NTrial=30
Split Flow Tol=0.02
Split Flow Ratio=0.02
Log Output Level=0
Friction Slope Method=1
Unsteady Friction Slope Method=2
Unsteady Bridges Friction Slope Method=1
Global Log Level=0
CheckData=False
Run HTab=0
Run UNet=0
Run PostProcess=0
UNET Theta=0
UNET Theta Warmup=0
UNET ZTol=0
UNET ZSATol=0
UNET MxIter=0
UNET MaxInSteps=0
UNET DtIC=0
UNET DtMin=0
UNET MaxCRTS=0
UNET WFStab=0
UNET SFStab=0
UNET WFX=0
UNET SFX=0
UNET DSS MLevel=0
UNET DZMax Abort=0
UNET Convert EG Bridges=0
UNET Use Existing IB Tables=0
UNET Froude Limit=0
UNET Froude Power=0
Write IC File=0
Echo Input=False
Echo Output=False
Write Detailed=0

--- MissouriFk.f01 (steady flow) ---

Flow Title=NFF Regression Equation
Program Version=4.10
Number of Profiles= 1
Profile Names=P100yr
River Rch & RM=MissouriFk,Main            ,1670.7
933.0796
River Rch & RM=MissouriFk,Main            ,470.7
953.4482
River Rch & RM=MissouriFk,Main            ,248.3
956.3408
Boundary for River Rch & Prof#=MissouriFk,Main            , 1
Up Type= 0
Dn Type= 3
Dn Slope=0.01116
DSS Import GetInterval= 0
DSS Import GetPeak= 0
DSS Import FillOption= 0

--- MissouriFk.g01 (geometry) ---

Geom Title=USGS 3m DEM
Program Version=4.10

River Reach=MissouriFk      ,Main
Reach XY= 30
     1859186.673      635934.005     1859240.513      635897.536
     1859271.776      635873.224     1859304.775      635850.648
     1859360.012      635801.518     1859398.563       635777.71
     1859455.877      635729.084     1859561.822      635645.726
     1859605.244      635590.153     1859652.137      635558.894
     1859745.923       635510.27     1859779.815       635495.32
      1859818.43      635470.372     1859864.026       635423.44
     1859924.816      635341.816     1859957.817      635284.505
     1859979.487       635241.17     1859987.668      635229.331
     1860063.763      635168.149     1860088.078      635155.994
     1860115.867      635133.417     1860140.183      635102.157
     1860171.446      635070.898     1860197.499      635034.427
     1860247.868      634956.277     1860306.919      634911.125
     1860338.181      634897.233     1860388.547      634895.498
     1860416.334      634902.446     1860441.621      634903.291

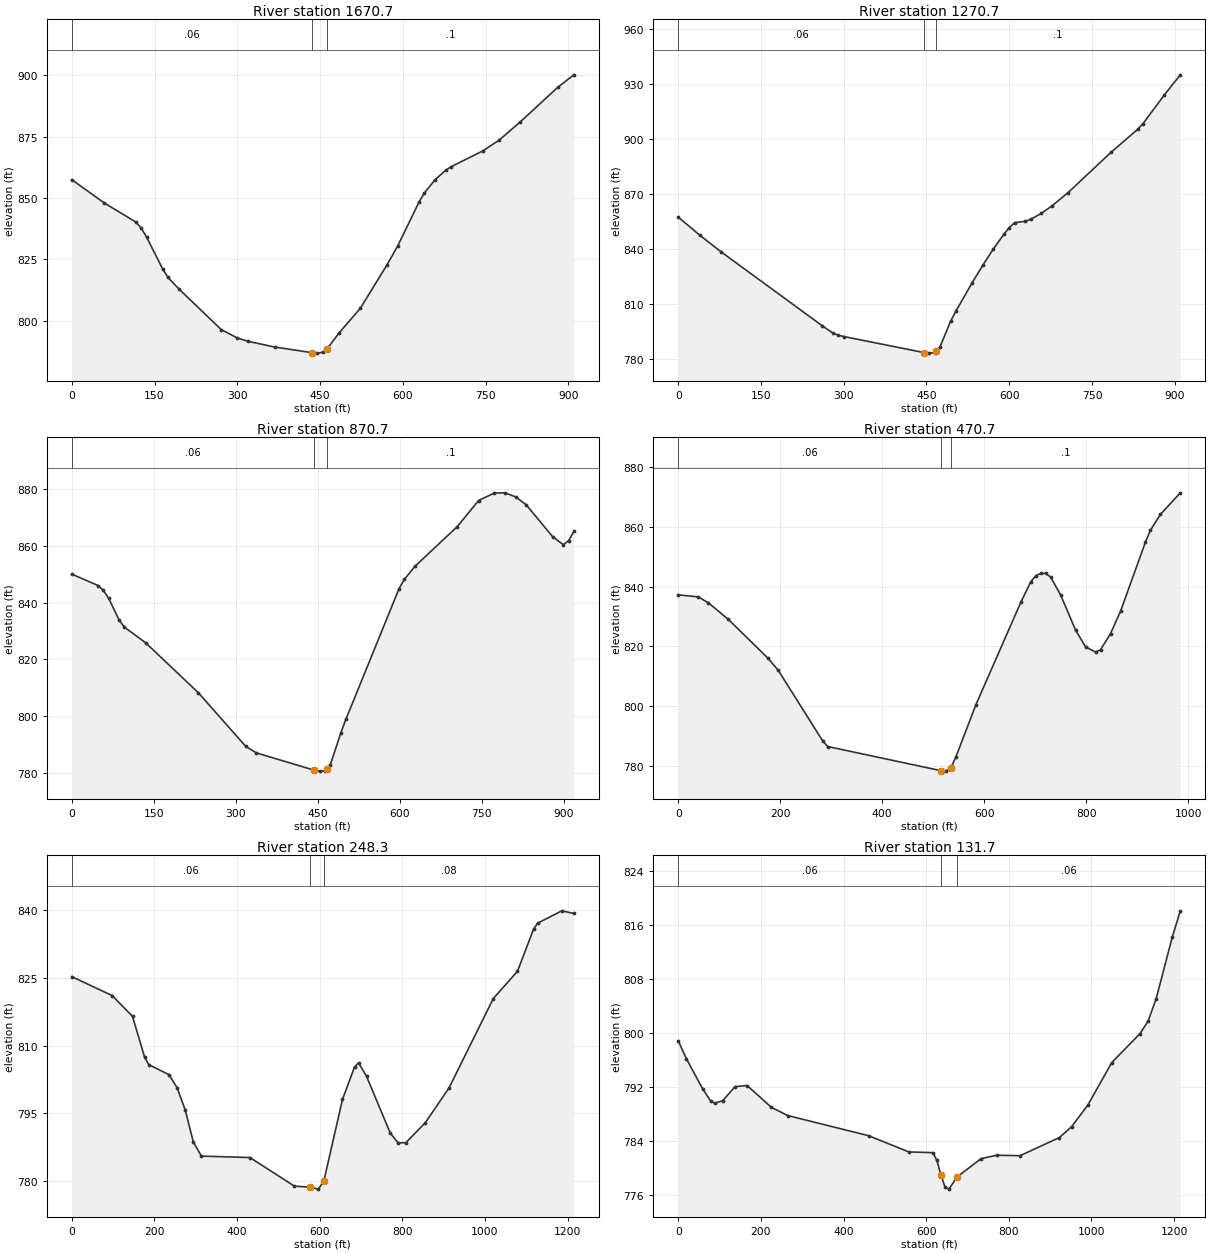
Type RM Length L Ch R = 1 ,1670.7  ,401.2,400,398
XS GIS Cut Line= 3
     1859452.665      636303.292     1859194.913       635928.34
     1858937.161      635553.388
#Sta/Elev= 30
       0  857.53    58.1  848.15   116.2  840.24   125.8   837.8   135.5  834.19
   164.6   821.2   174.3  817.72   193.6  813.12   271.1   796.4   300.1  793.03
   319.5  791.65   367.9  789.33   435.6  787.04   445.3  786.85     455  787.19
   462.5  788.47     484  794.96   522.8  805.05   571.2  822.76   590.5  830.42
   629.3  848.36   638.9  852.03   658.3  857.48   677.7  861.35   687.3  862.78
   745.4  869.29   774.5  873.61   813.2  881.12     881  895.18     910  900.24
#Mann= 3 , 0 , 0
       0     .06       0   435.6    .045       0   462.5      .1       0
Bank Sta=435.6,462.5
XS Rating Curve= 0 ,0
Exp/Cntr=0.3,0.1

Type RM Length L Ch R = 1 ,1270.7  ,403,400,399
XS GIS Cut Line= 3
      1859791.59      636043.582     1859511.503      635685.034
     1859222.643      635333.329
#Sta/Elev= 30
       0  857.39    38.7  847.61    77.4  838.51   261.4  798.04   280.7   794.1
   290.4  792.93   300.1  792.27   445.3  783.52     455  783.21   464.7  783.41
  467.57  784.31   474.4  786.56   493.7  800.59   503.4  806.18   532.4  821.38
   551.8     831   571.2  840.02   590.6  848.17   600.2   851.7   609.9  854.37
   629.3  855.11     639  856.18   658.3  859.47   677.7  863.56   706.8  870.78
   784.2  892.64   832.6   905.2   842.3   908.3     881  923.93   910.1  934.97
#Mann= 3 , 0 , 0
       0     .06       0   445.3    .045       0  467.57      .1       0
Bank Sta=445.3,467.57
XS Rating Curve= 0 ,0
Exp/Cntr=0.3,0.1

Type RM Length L Ch R = 1 ,870.7   ,396.9,400,400.9
XS GIS Cut Line= 3
      1860157.89      635771.454      1859832.78      635455.601
     1859523.299      635108.857
#Sta/Elev= 30
       0  850.04    48.2  846.02    57.9  844.28    67.5  841.51    86.8  833.76
    96.4  831.32     135  825.85   231.5   808.2   318.3  789.26   337.6     787
   443.6  780.88   453.3  780.57     463  780.62  466.04  781.31   472.6  782.69
     492   794.1   501.7  799.08   598.5  844.96   608.2   848.2   627.6  852.82
     705  866.83   743.8     876   772.8  878.65   792.2  878.71   811.5  877.29
   830.9   874.5   879.3  863.23   898.7  860.43   908.4  861.83     918  865.11
#Mann= 3 , 0 , 0
       0     .06       0   443.6    .045       0  466.04      .1       0
Bank Sta=443.6,466.04
XS Rating Curve= 0 ,0
Exp/Cntr=0.3,0.1

Type RM Length L Ch R = 1 ,470.7   ,212.8,222.5,233.3
XS GIS Cut Line= 4
     1860366.065      635597.483     1860261.946      635375.942
     1860087.703      635156.181     1859796.535      634800.617
#Sta/Elev= 30
       0  837.28    39.2   836.6    58.8  834.64    97.9  829.12   176.2  816.01
   195.8  812.08   283.5  788.29   293.1  786.45   515.6  778.34   525.2   778.2
     535  779.37   544.8  783.05   583.9  800.46   671.9  834.76   691.5  841.66
   701.2  843.64     711  844.48   720.8  844.45   730.6   843.2   750.1  837.22
   779.5   825.4     799  819.85   818.6  818.08   828.4   818.9   847.9  824.28
   867.5  831.76   916.4  854.96   926.2  858.92   945.7  864.24   984.8  871.47
#Mann= 3 , 0 , 0
       0     .06       0   515.6    .045       0     535      .1       0
Bank Sta=515.6,535
XS Rating Curve= 0 ,0
Exp/Cntr=0.3,0.1

Type RM Length L Ch R = 1 ,248.3   ,118.5,116.6,113.8
XS GIS Cut Line= 5
     1860430.586      635558.717     1860257.409      635069.134
     1860184.492      634858.196     1860141.523      634713.665
      1860026.94      634412.884
#Sta/Elev= 30
       0  825.28      98  821.05     147  816.46   176.4   807.4   186.2  805.78
   235.2  803.55   254.8  800.66   274.4  795.76     294   788.7   313.6   785.5
   431.1  785.18   538.7  778.85   577.5   778.6   596.9  778.18  610.13  780.01
   655.2  798.08   684.3  805.23     694  806.19   713.4  803.18   770.8   790.6
   789.6  788.45   808.5  788.47   855.6   792.9   912.8  800.57  1020.1  820.41
  1078.6  826.44  1117.6  835.79  1127.4  837.11  1185.9  839.85  1215.1  839.27
#Mann= 3 , 0 , 0
       0     .06       0   577.5    .045       0  610.13     .08       0
Bank Sta=577.5,610.13
XS Rating Curve= 0 ,0
Exp/Cntr=0.3,0.1

Type RM Length L Ch R = 1 ,131.7   ,123.3,131.7,140.1
XS GIS Cut Line= 5
     1860530.128      635524.566     1860356.951      635034.983
     1860284.034      634824.045     1860241.065      634679.514
     1860126.482      634378.733
#Sta/Elev= 30
       0  798.86    19.6  796.22    58.8  791.76    78.4  789.94    88.2   789.6
   107.8  789.98   137.2  792.05   166.6  792.23   225.4     789   264.6  787.78
   460.5  784.79   558.1  782.38   616.4  782.27     626  781.12   635.8  778.94
   645.5   777.2   655.2  776.86   674.6  778.66   732.8  781.38   770.8  781.89
   827.3  781.82   922.5  784.51   951.8  786.11   990.8  789.28  1049.3  795.64
  1117.6  799.93  1137.1  801.78  1156.6  805.09  1195.6  814.23  1215.1  818.14
#Mann= 3 , 0 , 0
       0     .06       0   635.8    .045       0   674.6     .06       0
Bank Sta=635.8,674.6
XS Rating Curve= 0 ,0
Exp/Cntr=0.3,0.1

Chan Stop Cuts=-1
Use User Specified Reach Order=0
Composite Channel Slope=5